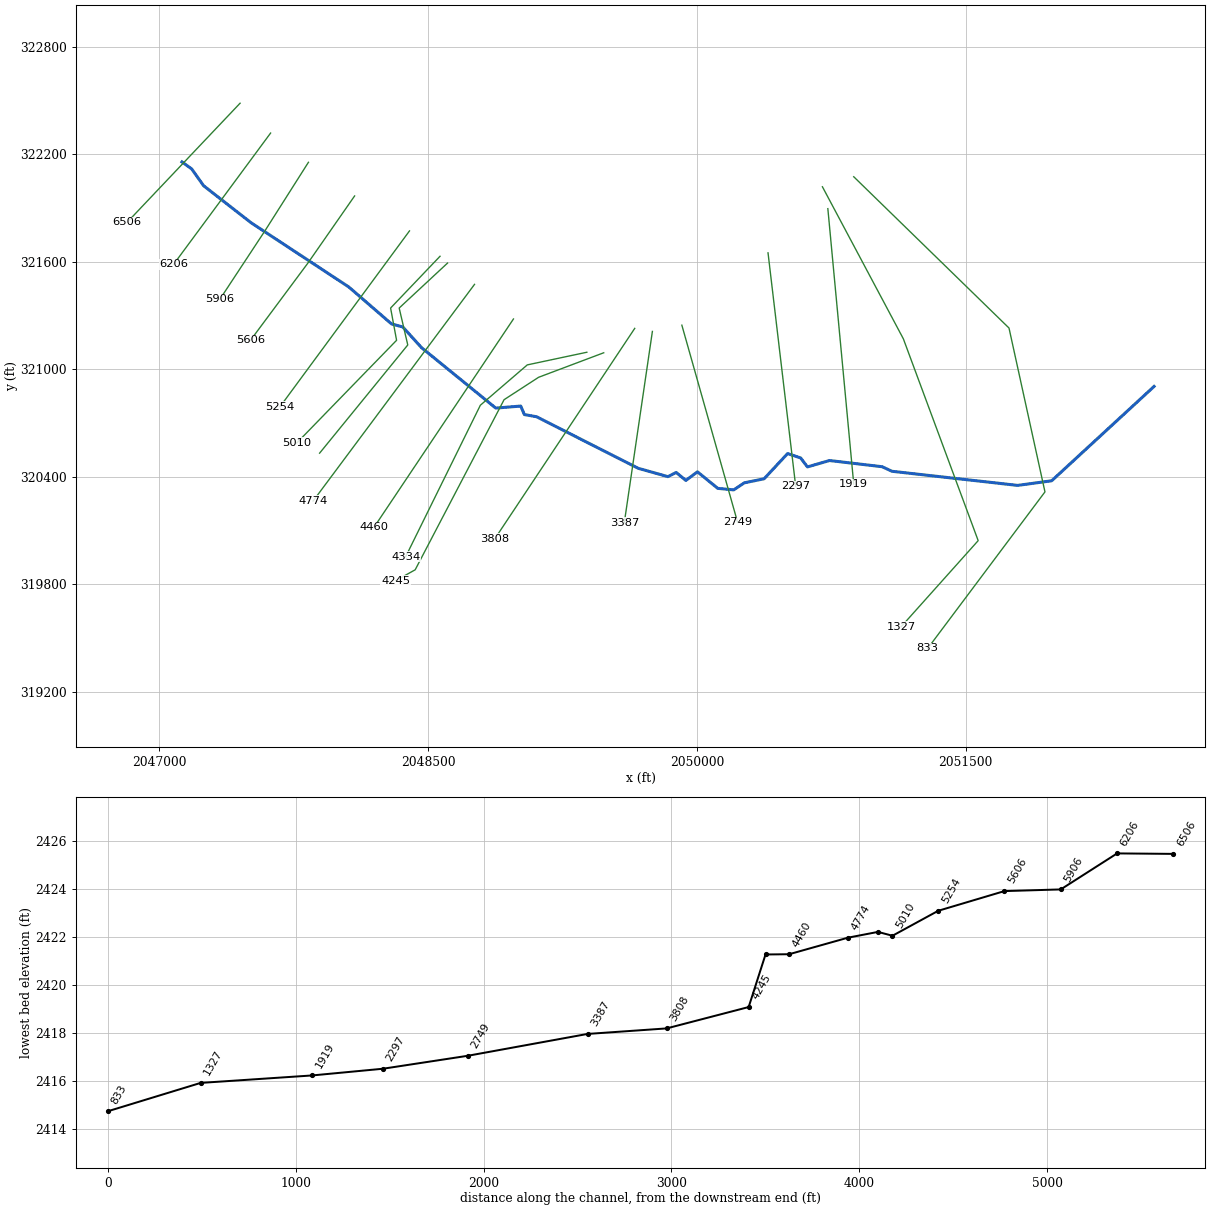
--- EAGLEBR.prj (project) ---

Proj Title=EAGLEBR
Current Plan=p01
Default Exp/Contr=0.3,0.1
English Units
Geom File=g01
Flow File=f01
Plan File=p01
Y Axis Title=Elevation
X Axis Title(PF)=Main Channel Distance
X Axis Title(XS)=Station
BEGIN DESCRIPTION:
Stream Name- Eagle Branch
Flood Zone: Zone A
Greenbrier County, WV
County-Wide Study
WVDHSEM-2018-3, Flood Risk Project
HEC-RAS Version: 5.0.7
General Notes:
For the Hydrology regression was used.
END DESCRIPTION:
DSS File=dss
DSS Export Rating Curves= 0
DSS Export Rating Curve Sorted= 0
DSS Export Volume Flow Curves= 0
DXF Filename=..\H2c.
DXF OffsetX= 0
DXF OffsetY= 0
DXF ScaleX= 1
DXF ScaleY= 10

--- EAGLEBR.p01 (plan) ---

Plan Title=Floodplain
Program Version=5.07
Short Identifier=Floodplain
Geom File=g01
Flow File=f01
Subcritical Flow
K Sum by GR= 0
Std Step Tol= 0.01
Critical Tol= 0.01
Num of Std Step Trials= 20
Max Error Tol= 0.3
Flow Tol Ratio= 0.001
Split Flow NTrial= 30
Split Flow Tol= 0.02
Split Flow Ratio= 0.02
Log Output Level= 0
Friction Slope Method= 1
Unsteady Friction Slope Method= 2
Unsteady Bridges Friction Slope Method= 1
Parabolic Critical Depth
Global Vel Dist= 0 , 0 , 0
Global Log Level= 0
CheckData=True
Encroach Param=-1 ,0,0, 0
Computation Interval=1MIN
Output Interval=1HOUR
Instantaneous Interval=1HOUR
Mapping Interval=1HOUR
Computation Time Step Use Courant=        0
Computation Time Step Use Time Series=    0
Computation Time Step Count To Double=0
Computation Time Step Max Doubling=0
Computation Time Step Max Halving=0
Computation Time Step Residence Courant=0
Run HTab= 0
Run UNet= 0
Run Sediment= 0
Run PostProcess= 0
Run WQNet= 0
Run RASMapper=-1
UNET Theta= 1
UNET Theta Warmup= 1
UNET ZTol= 0.02
UNET ZSATol= 0.02
UNET MxIter= 20
UNET Max Iter WO Improvement= 0
UNET MaxInSteps= 0
UNET DtIC= 0
UNET DtMin= 0
UNET MaxCRTS= 20
UNET WFStab= 2
UNET SFStab= 1
UNET WFX= 1
UNET SFX= 1
UNET 1D Methodology=Finite Difference
UNET DSS MLevel= 4
UNET Pardiso=0
UNET DZMax Abort= 100
UNET Use Existing IB Tables=-1
UNET Froude Reduction=False
UNET Froude Limit= 0.8
UNET Froude Power= 4
UNET D1 Cores= 0
UNET D2 Coriolis=0
UNET D2 Cores= 0
UNET D2 Theta= 1
UNET D2 Theta Warmup= 1
UNET D2 Z Tol= 0.01
UNET D2 Volume Tol= 0.01
UNET D2 Max Iterations= 20
UNET D2 Equation= 0
UNET D2 RampUpFraction=0.1
UNET D2 TimeSlices= 1
UNET D2 BCVolumeCheck=0
UNET D1D2 MaxIter= 0
UNET D1D2 ZTol=0.01
UNET D1D2 QTol=0.1
UNET D1D2 MinQTol=1
DSS File=dss
Write IC File= 0
Write IC File at Fixed DateTime=0
Write IC File at Sim End=0
Echo Input=False
Echo Parameters=False
Echo Output=False
Write Detailed= 0
HDF Write Warmup=0
HDF Write Time Slices=0
HDF Flush=0
HDF Face Node Velocities=0
HDF Compression= 1
HDF Chunk Size= 1
HDF Spatial Parts= 1
HDF Use Max Rows=0
HDF Fixed Rows= 1
Calibration Method= 0
Calibration Iterations= 20
Calibration Max Change=0.05
Calibration Tolerance=0.2
Calibration Maximum=1.5
Calibration Minimum=0.5
Calibration Optimization Method= 1
WQ AD Non Conservative
WQ ULTIMATE=-1
WQ Max Comp Step=1HOUR
WQ Output Interval=15MIN
WQ Output Selected Increments= 0
WQ Output face flow=0
WQ Output face velocity=0
WQ Output face area=0
WQ Output face dispersion=0
WQ Output cell volume=0
WQ Output cell surface area=0
WQ Output cell continuity=0
WQ Output cumulative cell continuity=0
WQ Output face conc=0
WQ Output face dconc_dx=0
WQ Output face courant=0
WQ Output face peclet=0
WQ Output face adv mass=0
WQ Output face disp mass=0
WQ Output cell mass=0
WQ Output cell source sink temp=0
WQ Output nsm pathways=0
WQ Output nsm derived pathways=0
WQ Output MaxMinRange=-1
WQ Daily Max Min Mean=-1
WQ Daily Range=0
WQ Daily Time=0
WQ Create Restart=0
WQ Fixed Restart=0
WQ System Summary=0
WQ Write To DSS=0
WQ Use Fixed Temperature=0
Sorting and Armoring Iterations= 10
XS Update Threshold= 0.02
Bed Roughness Predictor= 0
Hydraulics Update Threshold= 0.02
Energy Slope Method= 1
Volume Change Method= 1
Sediment Retention Method= 0
XS Weighting Method= 0
Number of US Weighted Cross Sections= 1
Number of DS Weighted Cross Sections= 1
Upstream XS Weight=0
Main XS Weight=1
Downstream XS Weight=0
Number of DS XS's Weighted with US Boundary= 1
Upstream Boundary Weight= 1
Weight of XSs Associated with US Boundary= 0
Number of US XS's Weighted with DS Boundary= 1
Downstream Boundary Weight= 0.5
Weight of XSs Associated with DS Boundary= 0.5
Percentile Method= 0
Sediment Output Level= 3
Mass or Volume Output= 0
Output Increment Type= 1
Profile and TS Output Increment= 1
XS Output Flag= 0
XS Output Increment= 10
Write Gradation File= 0
Read Gradation Hotstart= 0
Write HDF5 File= 1
Write Binary Output= 1
Write DSS Sediment File= 0
SV Curve= 0
Specific Gage Flag= 0

--- EAGLEBR.f01 (steady flow) ---

Flow Title=H2c
Program Version=5.07
Number of Profiles= 6
Profile Names=f1p,f10p,f4p,f2p,f02p,f1pplus
River Rch & RM=EAGLEBR,Main            ,6506
     609     322     428     516     849     900
River Rch & RM=EAGLEBR,Main            ,3808
     713     380     503     605     992    1050
Boundary for River Rch & Prof#=EAGLEBR,Main            , 1
Up Type= 0
Dn Type= 3
Dn Slope=0.00158
Boundary for River Rch & Prof#=EAGLEBR,Main            , 2
Up Type= 0
Dn Type= 3
Dn Slope=0.00158
Boundary for River Rch & Prof#=EAGLEBR,Main            , 3
Up Type= 0
Dn Type= 3
Dn Slope=0.00158
Boundary for River Rch & Prof#=EAGLEBR,Main            , 4
Up Type= 0
Dn Type= 3
Dn Slope=0.00158
Boundary for River Rch & Prof#=EAGLEBR,Main            , 5
Up Type= 0
Dn Type= 3
Dn Slope=0.00158
Boundary for River Rch & Prof#=EAGLEBR,Main            , 6
Up Type= 0
Dn Type= 3
Dn Slope=0.00158
DSS Import GetInterval= 0
DSS Import GetPeak= 0
DSS Import FillOption= 0

--- EAGLEBR.g01 (geometry) ---

Geom Title=H2c
Program Version=5.07

River Reach=EAGLEBR         ,Main
Reach XY= 30
 2047126.4089395322156.5548967272047180.73560238322117.419148162
2047247.14032522322023.6811466372047512.11125198 321817.15531297
2048057.41823223321458.6583266712048295.61079443321252.659025345
2048358.73640236321235.3733814622048463.30488765321120.061234772
2048877.55782728320782.8399490552049016.76984501320794.125378929
2049037.20700391320746.7774123652049105.52899708320734.419617578
2049672.31198403320446.8785259872049838.22456515320400.191316697
2049884.09353469320423.6459363462049938.28684579320379.135551244
2050003.01637512320427.2138671432050116.25532205320334.941741988
2050205.32765032 320326.479816752050264.57399448320365.854012015
 2050374.8237776320388.3865850882050506.11284839320529.274840153
2050578.99856934320504.4011750652050616.56223401320454.622750068
2050739.66913602320490.2992830812051033.35864405320455.723774223
2051088.67960124 320430.144272222051789.51634664320351.458860004
2051979.49095683320377.2846127162052550.85288168320903.737434447

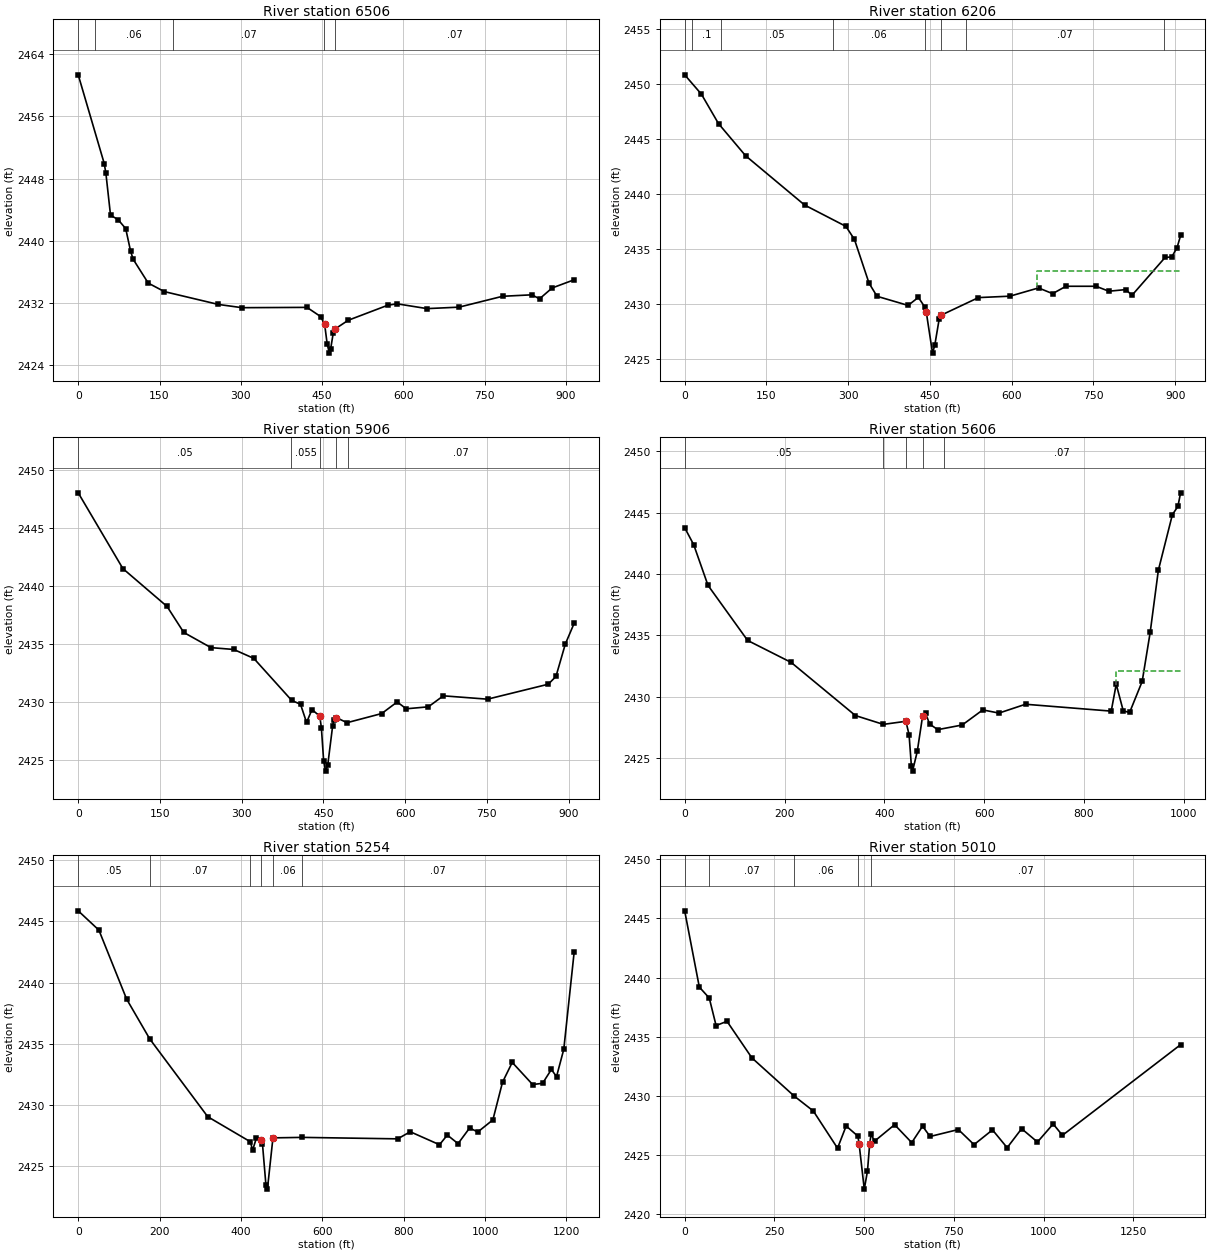
Type RM Length L Ch R = 1 ,6506    ,297.7,300,301.3
XS GIS Cut Line= 3
     2047450.786      322484.007     2047133.823      322149.876
     2046821.254      321820.173
#Sta/Elev= 30
       0 2461.37      48 2449.93    51.1 2448.65    59.6 2443.27    73.5  2442.7
    87.6 2441.54    96.7 2438.61   101.4 2437.58   129.2 2434.51   159.1 2433.41
   258.5 2431.76   302.1 2431.34     422 2431.38   447.1  2430.2   454.6  2429.2
   459.4  2426.6   463.4 2425.48   465.7 2426.03   470.4 2428.04   473.7 2428.59
   498.2 2429.72   571.2 2431.66   588.2 2431.84   643.5 2431.22   702.6 2431.41
   782.8 2432.81     837    2433     851 2432.48   874.2 2433.88   914.9 2434.94
#Mann= 5 ,-1 , 0
       0      .1       0   30.98     .06       0  175.11     .07       0
   453.1    .045       0   473.7     .07       0
Bank Sta=454.6,473.7
XS Rating Curve= 0 ,0
Exp/Cntr=0.3,0.1

Type RM Length L Ch R = 1 ,6206    ,299.1,300,300.9
XS GIS Cut Line= 3
     2047620.992      322317.388     2047350.733      321951.348
     2047080.332      321585.414
#Sta/Elev= 30
       0 2450.81    30.7 2449.05    62.1 2446.37   111.8 2443.45     220 2438.97
   295.8 2437.03   311.5 2435.84   338.3 2431.86   352.9 2430.67   409.9 2429.84
   428.8 2430.57   440.6 2429.69   443.3 2429.23   454.8  2425.5   458.9 2426.22
     467  2428.6     471 2428.96     539 2430.55   596.9 2430.68   649.3 2431.43
   675.1 2430.91   699.6 2431.58   754.9 2431.58   778.3 2431.13   809.7 2431.28
   820.6 2430.75   881.5  2434.2   893.8 2434.25   903.5  2435.1     910  2436.2
#Mann= 8 ,-1 , 0
       0     .05       0   12.74      .1       0   67.34     .05       0
   272.6     .06       0   440.6    .045       0     471     .06       0
   515.5     .07       0   879.8     .12       0
#XS Ineff= 2 , 0
                          646.67         2432.95
Permanent Ineff=
       F       F
Bank Sta=443.3,471
XS Rating Curve= 0 ,0
Exp/Cntr=0.3,0.1

Type RM Length L Ch R = 1 ,5906    ,300.4,300,298.8
XS GIS Cut Line= 3
     2047832.244      322154.394     2047588.464      321770.299
     2047338.111      321390.094
#Sta/Elev= 30
       0 2448.02      82 2441.48   163.1 2438.21   193.7 2435.97   243.6 2434.66
   285.5  2434.5   322.3 2433.73   391.9  2430.1     408 2429.77   419.1  2428.2
     429 2429.31   443.3 2428.75   446.3 2427.74   450.4 2424.91     454    2424
   457.9  2424.5     467 2427.92   469.4 2428.44   473.7 2428.62   493.3 2428.18
     557 2428.97   585.4 2429.97     602 2429.38   642.6 2429.55   670.1  2430.5
   751.2 2430.21   862.6  2431.5   876.8 2432.17     894 2434.97   910.2 2436.76
#Mann= 5 ,-1 , 0
       0     .05       0  391.31    .055       0   443.3    .045       0
   473.7     .06       0   495.3     .07       0
Bank Sta=443.3,473.7
XS Rating Curve= 0 ,0
Exp/Cntr=0.3,0.1

Type RM Length L Ch R = 1 ,5606    ,352.4,352.3,352.5
XS GIS Cut Line= 3
     2048089.775      321966.462     2047829.552      321592.444
2047508.64151573321160.861128529
#Sta/Elev= 30
       0 2443.77    18.1 2442.38    46.7 2439.07   126.1 2434.58   213.3 2432.79
     342 2428.46   397.9 2427.74   443.1 2427.99   449.5 2426.91   454.2 2424.31
   456.5 2423.93   465.9 2425.53   476.6 2428.41   482.5 2428.66   490.6 2427.77
     507 2427.31     556 2427.69   597.2 2428.92   629.6 2428.66   682.8 2429.38
   854.5 2428.82   864.5 2431.01   878.6 2428.84   891.3 2428.71   916.5 2431.24
   932.5 2435.23   948.9  2440.3     977 2444.83     988  2445.5   993.5 2446.61
#Mann= 5 ,-1 , 0
       0     .05       0  398.25     .06       0   443.1    .045       0
   476.6     .06       0   519.3     .07       0
#XS Ineff= 2 , 0
                          864.86         2432.07
Permanent Ineff=
       F       F
Bank Sta=443.1,476.6
XS Rating Curve= 0 ,0
Exp/Cntr=0.3,0.1

Type RM Length L Ch R = 1 ,5254    ,223.1,243.6,247.1
XS GIS Cut Line= 2
2048396.13134587321771.5803251552047673.23007492320789.900519342
#Sta/Elev= 30
       0 2445.86    50.9 2444.28   118.9 2438.65   175.8 2435.39   318.4 2429.03
   423.3 2426.98   428.6 2426.29     438 2427.28   449.8 2427.16   452.9 2426.82
   461.5 2423.42   465.1 2423.11   478.7  2427.3   550.7 2427.34   785.3 2427.22
   816.2  2427.8   888.1 2426.74   907.3 2427.53   933.7 2426.83   962.2 2428.11
   982.2 2427.78  1019.3 2428.77    1043 2431.85  1066.9 2433.47    1117 2431.66
  1141.5 2431.76  1163.1 2432.89  1175.8 2432.31  1193.6 2434.54  1219.1 2442.48
#Mann= 6 ,-1 , 0
       0     .05       0   175.8     .07       0   423.3     .06       0
   449.8    .045       0   478.7     .06       0   550.7     .07       0
Bank Sta=449.8,478.7
XS Rating Curve= 0 ,0
Exp/Cntr(USF)=0,0
Exp/Cntr=0.5,0.3

Type RM Length L Ch R = 1 ,5010    ,62.1,77.3,76.1
XS GIS Cut Line= 4
2048566.45584334321629.9403484392048290.71521221321341.138318993
2048324.09434124 321161.181275522047766.80801307320587.931016069
#Sta/Elev= 30
       0 2445.65    40.8 2439.19    68.5 2438.26    87.5 2435.93   117.9 2436.29
   187.3 2433.19     305 2429.96   358.4 2428.69   425.9 2425.54   449.9 2427.42
   482.6 2426.56   485.9 2425.92   500.4 2422.07   509.3  2423.6   515.4 2425.88
   519.3 2426.71   529.3 2426.14   584.9 2427.53   632.6 2426.01   662.8  2427.4
   683.8 2426.53   762.5 2427.12   806.2 2425.84   857.6 2427.09   898.5 2425.58
   938.8 2427.19   982.9 2426.06  1026.7 2427.59  1052.5 2426.63  1381.8 2434.31
#Mann= 5 ,-1 , 0
       0     .05       0    68.5     .07       0     305     .06       0
   482.6    .045       0   519.3     .07       0
#XS Ineff= 2 , 0
          469.38    2426  534.55            2426
Permanent Ineff=
       F       F
Bank Sta=485.9,515.4
XS Rating Curve= 0 ,0
Exp/Cntr(USF)=0,0
Exp/Cntr=0.5,0.3

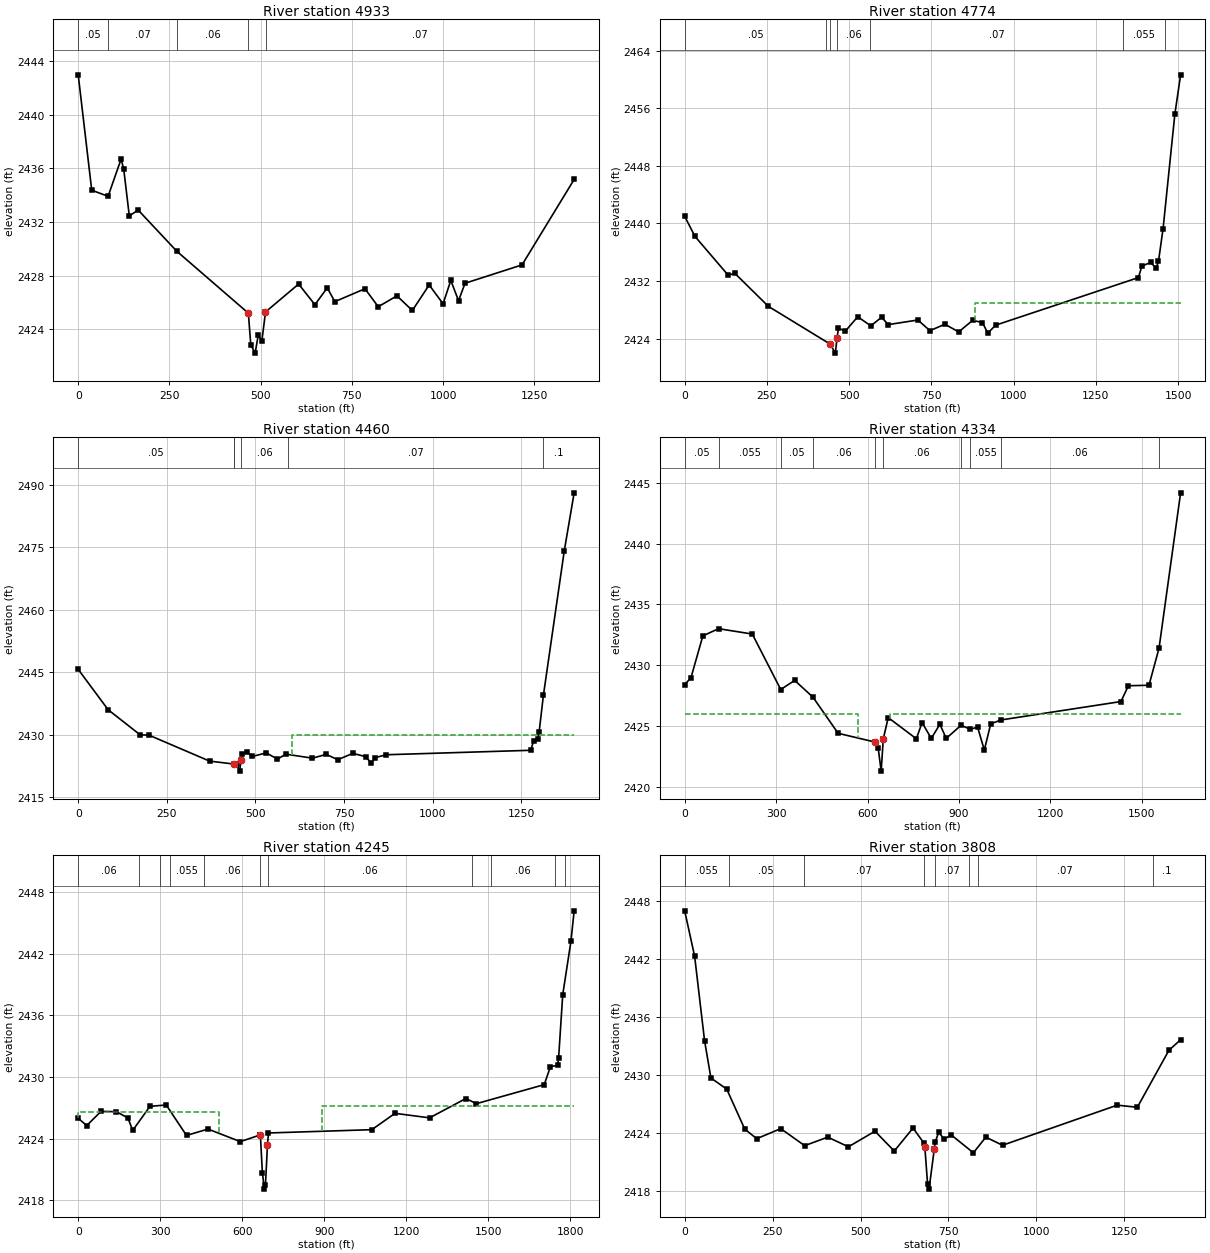
Type RM Length L Ch R = 1 ,4933    ,185.4,159.4,148.5
XS GIS Cut Line= 4
2048608.54257125321592.2074199682048338.60700604321341.138318993
2048386.49879987321135.0584788872047894.51946328320531.331623363
#Sta/Elev= 30
       0 2442.98      37 2434.38    81.8 2433.92   117.6  2436.7   124.8 2435.93
     140 2432.46   164.2  2432.9     270 2429.83   466.2 2425.21   472.9 2422.85
   484.9 2422.23   493.1 2423.56   503.2 2423.13   513.22425.277   513.3  2425.3
     604 2427.38   648.6 2425.84   682.4  2427.1   703.2 2426.07   785.8 2427.03
   822.1 2425.69   873.4  2426.5   915.6 2425.41   961.7 2427.31   999.8 2425.91
    1021 2427.65  1042.2 2426.14    1060 2427.44  1216.2 2428.81    1359 2435.18
#Mann= 5 ,-1 , 0
       0     .05       0    81.8     .07       0     270     .06       0
   466.2    .045       0   513.3     .07       0
Bank Sta=466.2,513.2
XS Rating Curve= 0 ,0
Exp/Cntr(USF)=0,0
Exp/Cntr=0.5,0.3

Type RM Length L Ch R = 1 ,4774    ,313.1,313.8,314.2
XS GIS Cut Line= 2
2048759.04439793321473.2534942272047858.18655902320264.291700728
#Sta/Elev= 30
       0 2440.99    31.3  2438.2   132.5  2432.8   152.3 2433.08   254.6 2428.48
   442.8 2423.23     458 2421.99   463.3 2424.11   467.4 2425.44   488.5 2425.05
     526 2427.04   565.9 2425.78   598.7 2426.97   618.8 2425.95     709 2426.59
   745.6 2425.11   790.9    2426   833.1 2424.94   875.3 2426.54   905.2 2426.24
   921.5 2424.76   945.1 2425.87  1379.4 2432.48  1389.9 2434.08  1416.6 2434.58
    1433  2433.8  1440.4 2434.73  1454.4 2439.29  1490.2 2455.19  1507.7 2460.64
#Mann= 7 ,-1 , 0
       0     .05       0  431.06     .06       0   442.8    .045       0
   463.3     .06       0  563.62     .07       0  1331.9    .055       0
 1460.11      .1       0
#XS Ineff= 2 , 0
                          881.35         2428.94
Permanent Ineff=
       F       F
Bank Sta=442.8,463.3
XS Rating Curve= 0 ,0
Exp/Cntr(USF)=0,0
Exp/Cntr=0.3,0.1

Type RM Length L Ch R = 1 ,4460    ,130.9,125.4,123.8
XS GIS Cut Line= 2
2048976.22451163 321280.088933042048198.08291683320117.564140803
#Sta/Elev= 30
       0 2445.71    84.4 2436.03   175.1 2429.98   198.8 2429.96   370.5 2423.71
   439.6 2422.99   447.5 2422.91   455.4  2421.3   459.4 2423.96   463.3 2425.36
   475.1 2425.94   490.9 2424.82   530.4 2425.67     562 2424.19   585.7 2425.37
   660.7 2424.41   699.3 2425.31   732.4 2424.04   774.6 2425.57   810.7 2424.77
   826.5 2423.24   838.4 2424.56   868.9 2425.23  1276.6  2426.3  1284.5 2428.58
  1296.3 2429.09    1300 2430.62  1312.1 2439.45  1370.9 2474.08  1398.9 2488.07
#Mann= 6 ,-1 , 0
       0     .05       0  438.73     .06       0   439.6    .045       0
   459.4     .06       0  592.45     .07       0 1311.26      .1       0
#XS Ineff= 2 , 0
                          603.22         2430.08
Permanent Ineff=
       F       F
Bank Sta=439.6,459.4
XS Rating Curve= 0 ,0
Exp/Cntr(USF)=0,0
Exp/Cntr=0.5,0.3

Type RM Length L Ch R = 1 ,4334    ,83,89.8,94
XS GIS Cut Line= 4
2049385.80197999321094.4743844232049053.35178985321023.865494483
2048791.51048966320798.7996578012048374.81382786319953.567112425
#Sta/Elev= 30
       0  2428.4    20.7 2428.97    59.6 2432.41   111.2    2433   221.9 2432.56
   315.2    2428     361 2428.75   421.3 2427.36   503.5  2424.4     623 2423.69
   634.9 2423.22   644.8 2421.29   651.8 2423.95   667.9 2425.69   760.3 2423.95
     779 2425.28   809.3 2423.98   837.5 2425.14   858.3 2423.98     907 2425.06
   937.6 2424.73   961.2 2424.91   983.3 2423.02  1004.4 2425.18  1038.7  2425.5
  1431.6 2427.01  1456.1 2428.31  1523.7 2428.35  1556.6 2431.39  1627.5 2444.17
#Mann= 10 ,-1 , 0
       0     .05       0   111.2    .055       0   315.2     .05       0
   421.3     .06       0     623    .045       0   651.8     .06       0
     907     .07       0   937.6    .055       0  1038.7     .06       0
  1556.6     .05       0
#XS Ineff= 2 , 0
          569.88    2426  672.86            2426
Permanent Ineff=
       F       F
Bank Sta=623,651.8
XS Rating Curve= 0 ,0
Exp/Cntr(USF)=0,0
Exp/Cntr=0.5,0.3

Type RM Length L Ch R = 1 ,4245    ,424.3,436.9,417.3
XS GIS Cut Line= 5
2049479.94716657321091.5323473422049116.60558709320954.727623084
 2048923.9021583320829.6910471492048427.83080685319880.492175705
2048318.50168662319819.777740758
#Sta/Elev= 30
       0 2425.99    31.1 2425.28    83.4 2426.66   139.7 2426.63   181.8 2426.02
   199.3 2424.81   262.4 2427.15     322 2427.28   396.1 2424.32   474.7 2424.94
   592.9 2423.72   665.92424.371   666.3 2424.34   673.7 2420.67   681.2  2419.1
   684.9 2419.52   692.22423.385     696 2424.56    1074 2424.88  1158.7 2426.47
  1285.2 2426.03  1417.8 2427.91  1456.5 2427.41  1704.6 2429.26  1727.2 2431.01
  1753.4 2431.13  1757.2 2431.87  1772.2    2438  1802.2 2443.19    1814 2446.16
#Mann= 11 ,-1 , 0
       0     .06       0  221.34    .055       0  299.72     .06       0
  335.86    .055       0     461     .06       0   666.3    .045       0
     696     .06       0 1439.78     .05       0 1509.47     .06       0
 1743.41     .05       0 1780.99     .06       0
#XS Ineff= 2 , 0
          513.53 2426.59     891         2427.23
Permanent Ineff=
       F       F
Bank Sta=665.9,692.2
XS Rating Curve= 0 ,0
Exp/Cntr(USF)=0,0
Exp/Cntr=0.5,0.3

Type RM Length L Ch R = 1 ,3808    ,414.9,420.8,426
XS GIS Cut Line= 2
2049652.93991607321227.5927177592048872.02883907320053.199315129
#Sta/Elev= 30
       0 2447.01    28.3 2442.31    56.5 2433.58    74.6 2429.71   119.6 2428.56
   170.8 2424.42   204.9 2423.43   273.2 2424.47   341.2 2422.71   406.9 2423.59
   465.6 2422.59   541.2  2424.2     596 2422.15   649.3 2424.53   679.3 2423.03
     683 2422.56   690.8  2418.7   694.8 2418.21     7102422.394   712.1 2423.06
   722.4 2424.09   738.1 2423.38   757.9 2423.82     821 2421.97   856.4 2423.59
   903.8 2422.75    1230  2426.9  1287.2 2426.68  1377.1 2432.58  1410.3 2433.67
#Mann= 8 ,-1 , 0
       0    .055       0  125.15     .05       0  338.97     .07       0
   679.3    .045       0   712.1     .07       0  808.45    .055       0
  833.46     .07       0  1330.5      .1       0
Bank Sta=683,710
XS Rating Curve= 0 ,0
Exp/Cntr(USF)=0,0
Exp/Cntr=0.3,0.1

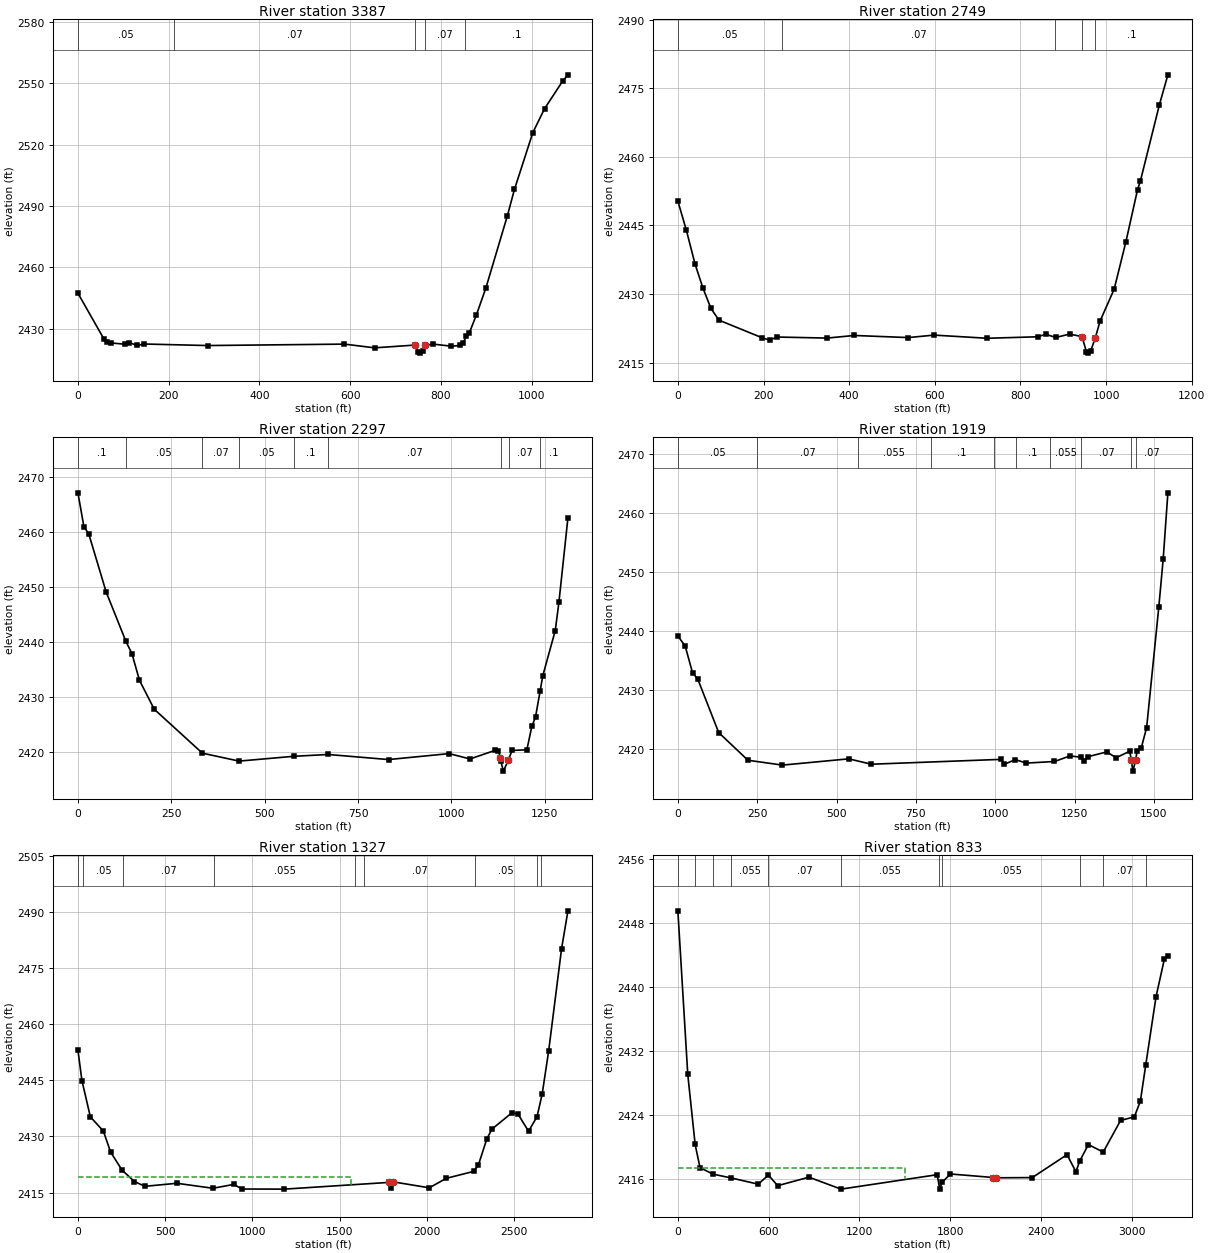
Type RM Length L Ch R = 1 ,3387    ,607.8,637.7,616.5
XS GIS Cut Line= 2
2049751.46619641321210.7024982742049594.52167906320141.985070654
#Sta/Elev= 30
       0 2447.31      57 2425.03    63.7 2423.64    73.6 2422.95   103.5 2422.34
   113.4 2423.17     130 2421.75   146.6 2422.44   285.7 2421.69   587.6 2422.39
   653.9 2420.57   743.5 2421.93   750.1 2418.59   753.4 2417.98   759.9 2418.85
   765.7 2421.84   783.3  2422.4     823 2421.37   842.9 2421.72   849.6 2423.03
   856.2  2426.3   862.8 2427.84   878.5 2436.73   899.3 2449.84   946.8 2485.25
   962.3  2498.1  1002.8 2525.87  1028.6 2537.56  1068.4 2551.03  1080.2 2554.16
#Mann= 5 ,-1 , 0
       0     .05       0  212.45     .07       0   743.5    .045       0
   765.7     .07       0  853.01      .1       0
Bank Sta=743.5,765.7
XS Rating Curve= 0 ,0
Exp/Cntr(USF)=0,0
Exp/Cntr=0.3,0.1

Type RM Length L Ch R = 1 ,2749    ,426.5,452,420.7
XS GIS Cut Line= 2
2049915.88426219321245.5790576832050227.28211406320144.476253469
#Sta/Elev= 30
       0 2450.32    19.9 2443.92    40.3 2436.49    58.7 2431.26    77.3 2426.84
    95.9 2424.28   197.2 2420.41   214.2 2419.91   231.5 2420.59   348.4 2420.36
     412 2420.93   538.1 2420.47   598.3 2421.01   722.2 2420.32   840.1 2420.64
   858.8 2421.19   882.7  2420.5   914.6 2421.23   943.8 2420.69   954.1 2417.37
   957.5 2417.07   964.3 2417.62   974.6 2420.36   986.3 2424.16  1018.9 2431.06
  1046.2 2441.38  1073.4 2452.77  1080.2 2454.73  1124.5 2471.36  1144.3 2477.91
#Mann= 5 ,-1 , 0
       0     .05       0  243.67     .07       0  880.96      .1       0
   943.8    .045       0   974.6      .1       0
Bank Sta=943.8,974.6
XS Rating Curve= 0 ,0
Exp/Cntr(USF)=0,0
Exp/Cntr=0.3,0.1

Type RM Length L Ch R = 1 ,2297    ,365.6,378.1,361.7
XS GIS Cut Line= 2
2050396.68254548321649.1506737082050551.13588001320346.262061481
#Sta/Elev= 30
       0 2467.05      16 2460.91    29.2 2459.56    75.5 2449.07   128.3 2440.12
   144.8 2437.82   164.7 2433.03   204.3 2427.77   333.2 2419.79   431.5 2418.35
   577.6 2419.22   670.2 2419.55   831.6 2418.63   994.1 2419.71  1049.9 2418.74
  1117.4 2420.31  1126.1 2420.22  1131.22418.866  1132.4 2418.29  1139.3 2416.53
  1152.5 2418.54  1162.4 2420.28  1202.1 2420.41  1215.3 2424.64  1225.2 2426.34
  1237.4 2431.03  1244.8 2433.87  1278.1 2442.05    1288 2447.26    1312 2462.51
#Mann= 9 ,-1 , 0
       0      .1       0   128.3     .05       0   333.2     .07       0
   431.5     .05       0   577.6      .1       0   670.2     .07       0
  1132.4    .045       0  1155.1     .07       0  1237.4      .1       0
Bank Sta=1131.2,1152.5
XS Rating Curve= 0 ,0
Exp/Cntr(USF)=0,0
Exp/Cntr=0.3,0.1

Type RM Length L Ch R = 1 ,1919    ,579.2,592.2,589
XS GIS Cut Line= 2
2050730.50104269321895.7777723892050874.98964595320358.717975556
#Sta/Elev= 30
       0 2439.13    23.1 2437.42    46.2  2432.9    62.7 2431.83   128.6 2422.78
   220.8 2418.09   329.6 2417.27   538.5 2418.33   609.7 2417.42  1018.3 2418.24
  1028.2  2417.4  1063.2  2418.2  1097.4 2417.61  1186.4 2417.88  1235.8 2418.83
  1268.7 2418.61  1278.6 2417.89  1291.8 2418.69  1351.1  2419.5  1380.8 2418.52
  1423.6 2419.62  1428.62418.084  1433.5 2416.25  1442.12418.069  1446.7 2419.64
  1459.9 2420.17  1476.9 2423.62  1515.1 2443.96  1529.1 2452.19  1543.8 2463.36
#Mann= 10 ,-1 , 0
       0     .05       0  250.25     .07       0  567.26    .055       0
   796.9      .1       0  994.75    .055       0 1064.48      .1       0
 1170.87    .055       0 1271.47     .07       0  1428.6    .045       0
 1442.04     .07       0
Bank Sta=1428.6,1442.1
XS Rating Curve= 0 ,0
Exp/Cntr(USF)=0,0
Exp/Cntr=0.3,0.1

Type RM Length L Ch R = 1 ,1327    ,495.5,493.8,491.4
XS GIS Cut Line= 4
2050700.27999858322017.7000078572051151.69587556321169.713173519
2051569.36103277320043.2829010412051139.03935565319562.335144252
#Sta/Elev= 30
       0 2453.07      23 2444.91    71.3 2435.24   145.6 2431.45   187.6 2425.81
   253.4 2420.98     324 2417.97   383.5 2416.69   566.8  2417.5   773.7 2416.17
   892.7  2417.2     941 2415.97  1183.3 2415.94  1779.9 2417.73  1792.4  2416.2
  1807.9 2417.87  2013.1 2416.29  2110.8 2418.83  2268.9 2420.69  2294.7 2422.44
  2342.7 2429.33  2372.2 2431.98  2485.2 2436.27  2520.3 2436.06  2581.9 2431.39
  2630.3 2435.29  2659.5 2441.22  2696.9  2452.8  2770.7 2480.05  2807.4 2490.25
#Mann= 9 ,-1 , 0
       0      .1       0    30.5     .05       0   260.9     .07       0
   781.3    .055       0  1586.1    .045       0  1638.6     .07       0
  2273.9     .05       0  2630.5     .07       0  2655.8      .1       0
#XS Ineff= 2 , 0
         1562.25 2419.12
Permanent Ineff=
       F       F
Bank Sta=1779.9,1807.9
XS Rating Curve= 0 ,0
Exp/Cntr(USF)=0,0
Exp/Cntr=0.3,0.1

Type RM Length L Ch R = 1 ,833     ,,,
XS GIS Cut Line= 4
2050874.98964595322073.7589446142051741.36766938321229.524768431
2051942.03215192320315.1954098852051287.41880088319441.409103467
#Sta/Elev= 30
       0 2449.49    65.4 2429.08   114.2 2420.33   146.3 2417.44   232.5 2416.63
   347.8 2416.17   531.1 2415.38   598.3 2416.52   659.3 2415.19   866.2 2416.25
  1077.8 2414.76  1713.2 2416.56  1729.7 2414.83    1748 2415.65  1800.7 2416.65
  2083.6 2416.21  2099.42416.174  2341.6  2416.2  2571.3 2419.06  2629.9 2416.93
  2655.7 2418.29  2712.5 2420.32  2810.3 2419.38  2925.2 2423.33  3015.9 2423.78
  3055.8 2425.73  3091.6 2430.28  3159.4 2438.78  3214.5 2443.47  3237.6 2443.89
#Mann= 11 ,-1 , 0
       0      .1       0   114.2     .05       0   232.5     .07       0
   347.8    .055       0   598.3     .07       0  1077.8    .055       0
  1722.8    .045       0    1748    .055       0  2655.7     .05       0
  2810.3     .07       0  3091.6      .1       0
#XS Ineff= 2 , 0
         1503.14 2417.41
Permanent Ineff=
       F       F
Bank Sta=2083.6,2099.4
XS Rating Curve= 0 ,0
Exp/Cntr(USF)=0,0
Exp/Cntr=0.3,0.1
LCMann Table=0

Chan Stop Cuts=-1
Use User Specified Reach Order=0
Composite Channel Slope=5